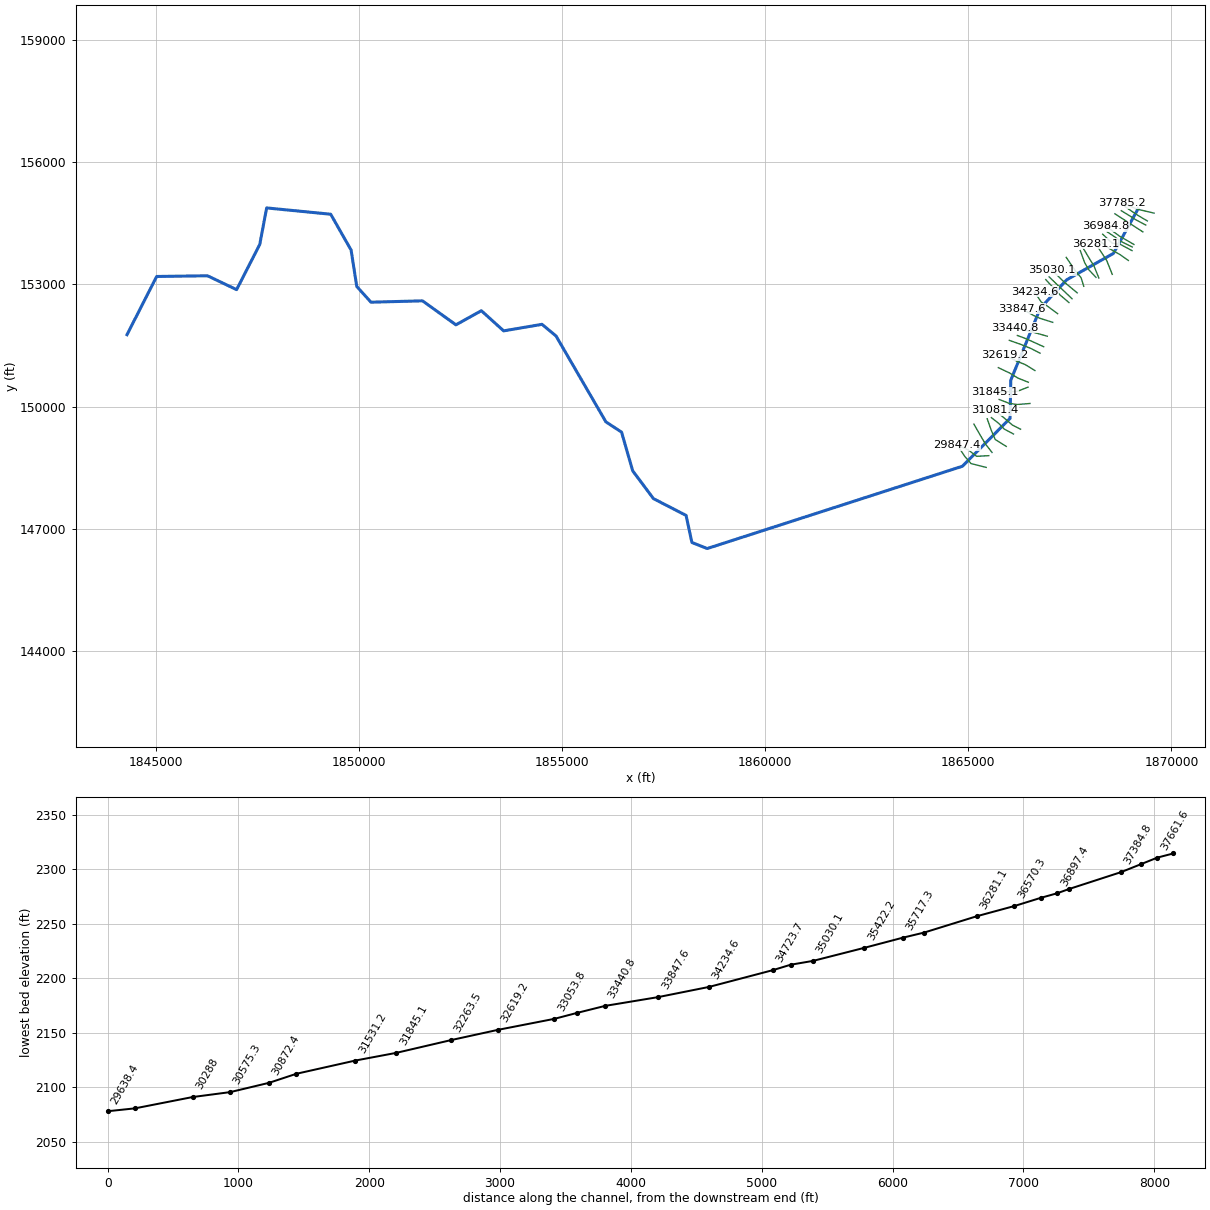
--- North Fork Elkhorn.prj (project) ---

Proj Title=NFElkhorn
Current Plan=p01
Default Exp/Contr=0,0
English Units
Geom File=g01
Flow File=f01
Plan File=p01
BEGIN DESCRIPTION:
END DESCRIPTION:
DSS Export Rating Curves= 0
DSS Export Rating Curve Sorted= 0
DSS Export Volume Flow Curves= 0
DXF OffsetX= 0
DXF OffsetY= 0
DXF ScaleX= 0
DXF ScaleY= 0

--- North Fork Elkhorn.p01 (plan) ---

Plan Title=Floodplain
Program Version=4.00
Geom File=g01
Flow File=f01
K Sum by GR=0
Std Step Tol=0.01
Critical Tol=0.01
Num of Std Step Trials=20
Max Error Tol=0.3
Flow Tol Ratio=0.001
Split Flow NTrial=30
Split Flow Tol=0.02
Split Flow Ratio=0.02
Log Output Level=0
Friction Slope Method=1
Unsteady Friction Slope Method=2
Unsteady Bridges Friction Slope Method=1
Global Log Level=0
CheckData=False
Run HTab=0
Run UNet=0
Run PostProcess=0
UNET Theta=0
UNET Theta Warmup=0
UNET ZTol=0
UNET ZSATol=0
UNET MxIter=0
UNET MaxInSteps=0
UNET DtIC=0
UNET DtMin=0
UNET MaxCRTS=0
UNET WFStab=0
UNET SFStab=0
UNET WFX=0
UNET SFX=0
UNET DSS MLevel=0
UNET DZMax Abort=0
UNET Convert EG Bridges=0
UNET Use Existing IB Tables=0
UNET Froude Limit=0
UNET Froude Power=0
Write IC File=0
Echo Input=False
Echo Output=False
Write Detailed=0

--- North Fork Elkhorn.f01 (steady flow) ---

Flow Title=NFF Regression Equation
Program Version=4.00
Number of Profiles=1
Profile Names=P100yr
River Rch & RM=North Fork El...,Main      ,37785.2
726.6457
River Rch & RM=North Fork El...,Main      ,36984.8
739.8585
River Rch & RM=North Fork El...,Main      ,35030.1
820.9980
River Rch & RM=North Fork El...,Main      ,33440.8
907.5493
River Rch & RM=North Fork El...,Main      ,30872.4
998.5567
River Rch & RM=North Fork El...,Main      ,30575.3
1675.385
River Rch & RM=North Fork El...,Main      ,28782.2
1745.902
Boundary for River Rch & Prof#=North Fork El...,Main      ,1
Up Type=0
Dn Type=3
Dn Slope=0.188409

--- North Fork Elkhorn.g01 (geometry) ---

Geom Title=USGS 10m DEM
Program Version=4.00

River Reach=NFElkhorn       ,Main
Reach XY= 30
     1869175.474      154852.941     1868570.304      153761.551
     1867423.992      153116.135     1866772.351      152417.949
     1866043.856      150648.838     1866027.115      149711.545
     1864853.212      148535.587     1858572.672      146515.457
     1858195.368      146663.609     1858052.062      147328.216
     1857248.673       147740.94     1856738.078      148422.742
     1856463.927      149373.269     1856079.009      149624.573
     1854850.679      151734.505     1854506.105       152019.93
     1853561.808      151859.316     1853012.815      152354.311
     1852386.983      152007.634     1851564.524      152596.615
     1850295.656      152563.338     1849946.453      152949.388
     1849806.604      153844.587     1849304.991      154723.039
     1847728.156      154877.759     1847558.975      153981.924
     1846988.693      152871.508     1846272.405      153212.073
     1845020.762      153194.751     1844291.368      151766.397

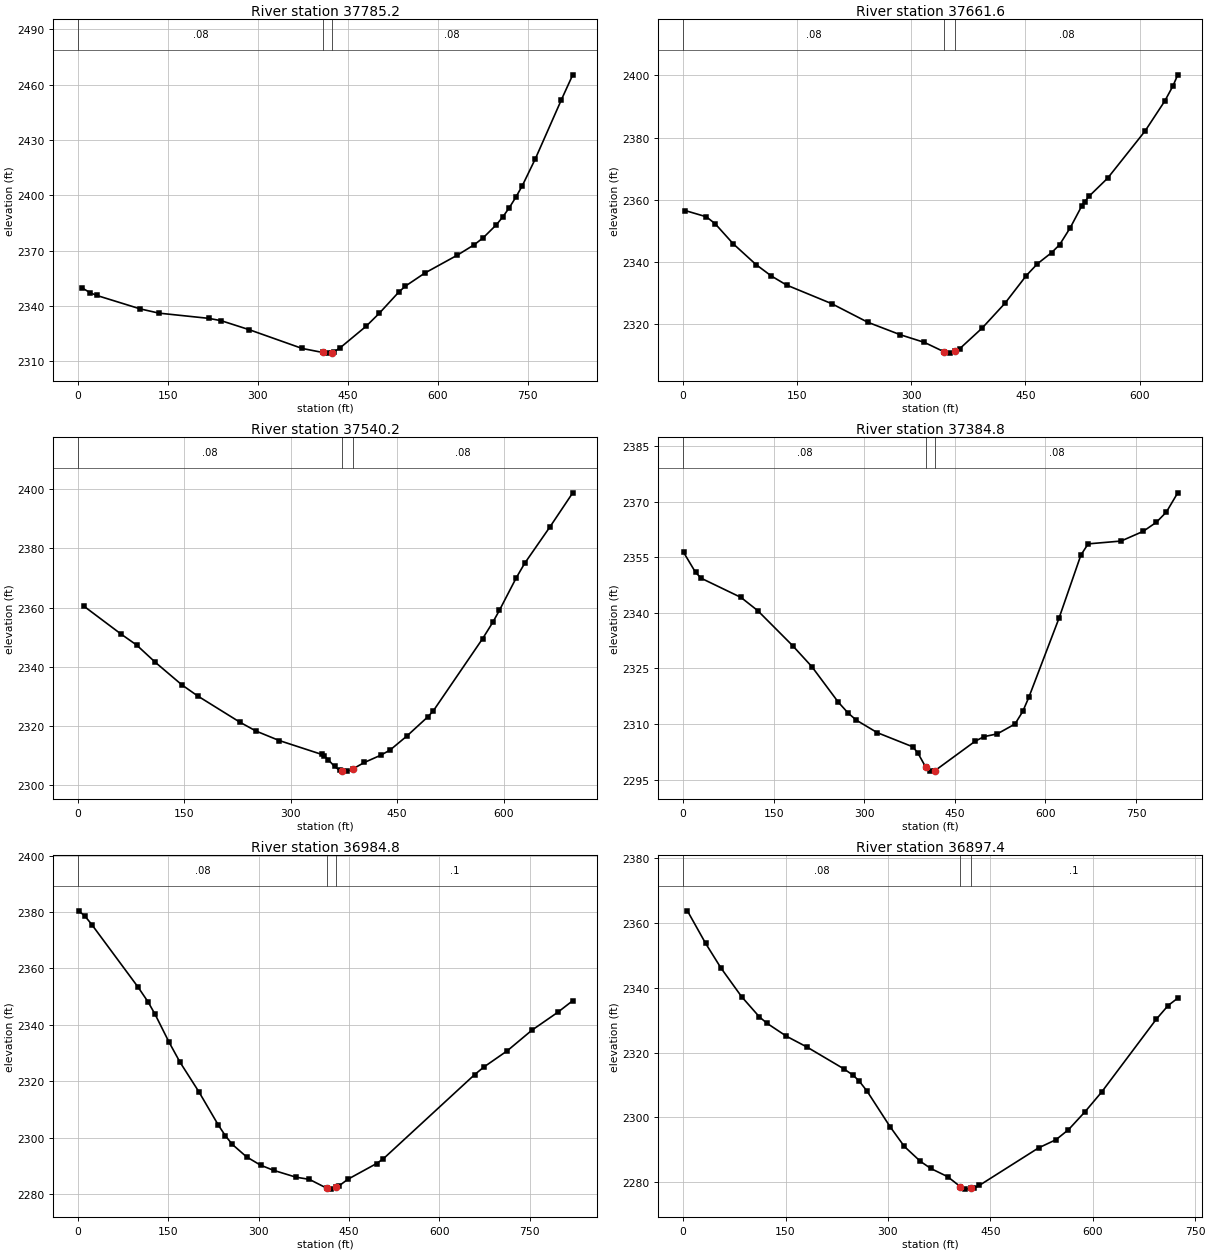
Type RM Length L Ch R = 1 ,37785.2 ,131.6,123.5,118.7
XS GIS Cut Line= 3
     1869570.931       154750.47     1869173.529      154843.131
     1868784.667      154994.411
#Sta/Elev= 30
       7 2349.72    20.6  2347.1    30.9 2345.74   103.6 2338.42   134.8 2336.12
   217.9 2333.29   238.7 2332.02   285.6 2327.12   373.7 2316.97   408.1 2314.78
   415.6 2314.43   423.1 2314.77   426.4 2315.01   437.3 2317.37   480.7 2329.08
   502.4 2336.04   534.9 2347.53   545.8 2350.73   578.4 2357.86   632.6 2367.56
   661.1 2373.28     676 2377.06   697.8 2384.07   708.6 2388.37   719.5 2393.39
   730.3 2399.04   741.2 2405.34   762.9 2419.92   806.3 2451.92   825.2 2465.39
#Mann= 3 , 0 , 0
       0     .08       0   408.1    .045       0   423.1     .08       0
Bank Sta=408.1,423.1
XS Rating Curve= 0 ,0
Exp/Cntr=0.3,0.1

Type RM Length L Ch R = 1 ,37661.6 ,121.4,121.5,121.6
XS GIS Cut Line= 4
     1869405.309      154559.007     1869195.897       154681.47
      1869053.84      154774.542     1868857.899      154909.251
#Sta/Elev= 30
     2.9 2356.46    30.5 2354.47    42.2  2352.2    65.7  2345.8    95.8 2339.08
   115.9 2335.41   135.9 2332.49   195.1 2326.51   242.6 2320.52   285.6 2316.47
   317.2 2314.01   342.7 2311.03   350.2 2310.56   357.7 2311.36   363.7 2312.01
   392.9 2318.59     423  2326.6   451.2 2335.56   465.8 2339.35   484.3 2342.91
   494.9 2345.48   508.9 2350.95     524 2357.95     528 2359.33   533.4 2361.04
     558  2366.9   607.1 2382.04   633.1 2391.73   643.9 2396.62   650.2 2400.19
#Mann= 3 , 0 , 0
       0     .08       0   342.7    .045       0   357.7     .08       0
Bank Sta=342.7,357.7
XS Rating Curve= 0 ,0
Exp/Cntr=0.3,0.1

Type RM Length L Ch R = 1 ,37540.2 ,155.3,155.4,155.4
XS GIS Cut Line= 4
     1869366.121      154457.362     1869106.499      154595.746
     1868976.688      154680.245     1868764.827      154810.056
#Sta/Elev= 30
     8.4 2360.41    60.9 2350.97    82.4 2347.35   108.9 2341.48   146.3 2333.87
   168.4 2330.15   228.5  2321.2   250.9 2318.25   283.5 2315.06   343.3 2310.38
   346.9 2309.87   352.6 2308.61   361.6 2306.28   368.9 2304.95     372 2304.83
   379.5 2304.71     387  2305.4   403.6 2307.63   426.8 2310.09   439.8 2311.81
   463.7 2316.58   493.4 2323.11   500.8 2325.04   570.5  2349.5   584.9 2355.05
   594.2 2359.08   617.9 2370.05   629.8 2374.96   665.4 2387.25   697.6 2398.78
#Mann= 3 , 0 , 0
       0     .08       0     372    .045       0     387     .08       0
Bank Sta=372,387
XS Rating Curve= 0 ,0
Exp/Cntr=0.3,0.1

Type RM Length L Ch R = 1 ,37384.8 ,398.9,400,398.7
XS GIS Cut Line= 3
     1869295.115      154289.937     1868951.014      154511.938
     1868606.912      154733.939
#Sta/Elev= 30
      .7 2356.34    20.6 2350.91      30 2349.33    95.8 2344.16   123.4 2340.61
   181.2 2331.16   213.2 2325.46   256.8 2315.91   273.4 2312.91     287 2311.01
   321.5 2307.65   380.3 2303.83   388.5  2302.2     402 2298.25   409.5 2297.27
     417  2297.4   483.6 2305.35   498.2 2306.58   520.2 2307.33   549.5 2309.99
   562.3 2313.37   572.5 2317.23   622.5 2338.61   658.6  2355.6   670.6 2358.62
   725.1 2359.38   761.7    2362   783.6 2364.45   800.1  2367.2     819  2372.4
#Mann= 3 , 0 , 0
       0     .08       0     402    .045       0     417     .08       0
Bank Sta=402,417
XS Rating Curve= 0 ,0
Exp/Cntr=0.3,0.1

Type RM Length L Ch R = 1 ,36984.8 ,90.9,87.4,86.4
XS GIS Cut Line= 3
     1869074.846      153981.144     1868717.686      154187.386
     1868387.693      154428.988
#Sta/Elev= 30
      .6 2380.44    10.9 2378.67    22.6 2375.58    99.4  2353.4     116 2348.16
   127.7 2343.75   151.1 2333.78   169.2 2326.72   200.5 2316.24   232.8 2304.43
   244.5 2300.64   256.2 2297.54   279.6 2293.16   302.9 2290.21   324.7 2288.36
   361.9 2285.93   383.9 2285.17   412.8 2282.04   420.3  2281.7   427.8 2282.34
   432.8  2282.8   448.1 2285.22   495.5 2290.77     507  2292.5   658.5 2322.34
     674 2325.05   712.5 2330.76   753.7 2338.11   796.4 2344.42   821.4 2348.56
#Mann= 3 , 0 , 0
       0     .08       0   412.8    .045       0   427.8      .1       0
Bank Sta=412.8,427.8
XS Rating Curve= 0 ,0
Exp/Cntr=0.3,0.1

Type RM Length L Ch R = 1 ,36897.4 ,112.3,125.8,139.2
XS GIS Cut Line= 4
     1869034.399      153919.137     1868723.649      154070.685
     1868605.778      154165.594      1868415.96      154291.119
#Sta/Elev= 30
     6.2 2363.64      33 2353.59    55.6 2345.97    85.5 2337.24   111.8 2330.95
   123.1 2328.97   151.4 2325.01   181.4 2321.69   235.6 2314.95   249.5 2312.93
   258.1 2311.16   269.4 2308.11   303.1 2297.17     324 2291.08   347.7 2286.46
   362.8 2284.29   387.5 2281.76     406 2278.71   413.5 2277.93     421 2278.13
   426.4 2278.25     434 2279.09   520.7 2290.63   546.2 2293.15   564.5 2296.23
   588.8 2301.77     613  2307.8   692.9 2330.19   710.5 2334.48   724.6 2336.75
#Mann= 3 , 0 , 0
       0     .08       0     406    .045       0     421      .1       0
Bank Sta=406,421
XS Rating Curve= 0 ,0
Exp/Cntr=0.3,0.1

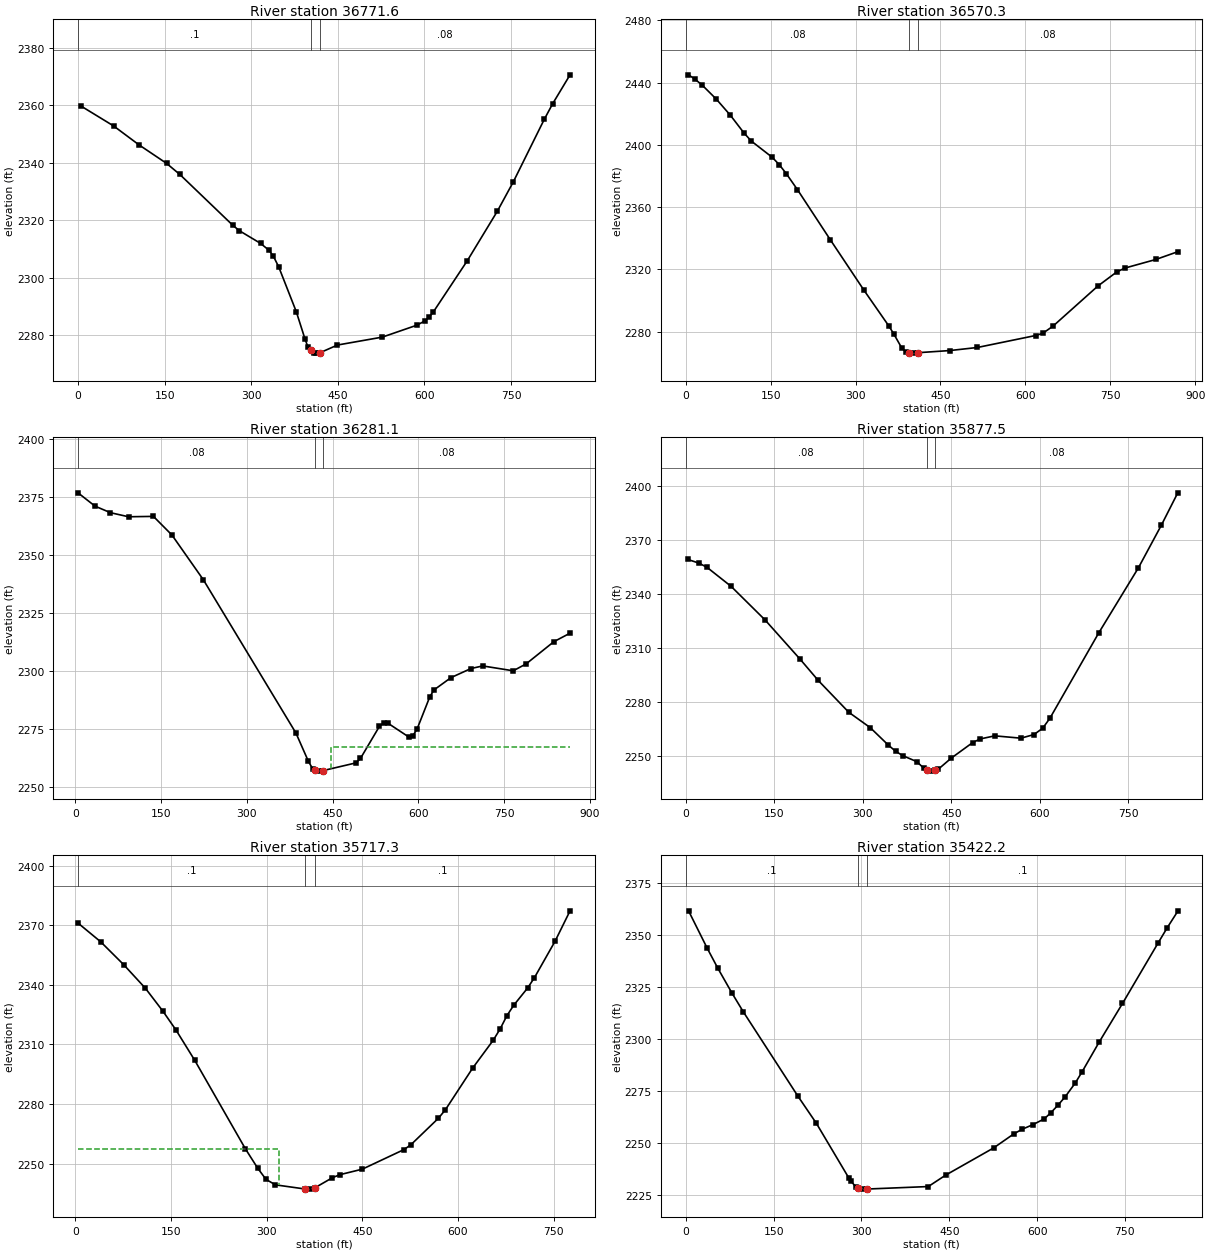
Type RM Length L Ch R = 1 ,36771.6 ,210.7,201.4,192.1
XS GIS Cut Line= 4
     1869028.725      153829.382     1868729.313      153989.553
     1868543.142      154011.013      1868305.91      154233.417
#Sta/Elev= 30
     4.3  2359.9    61.7 2352.85   105.4  2346.3   153.4 2339.81   176.4 2335.95
   268.1 2318.24   279.6 2316.34   316.1 2311.95     331  2309.5   338.5  2307.4
   347.5  2303.8     378 2288.14     393 2278.68   398.4 2275.71   403.8 2274.79
   408.5 2273.74   411.3 2273.71   418.8 2273.83   449.3 2276.53     527 2279.29
   586.6 2283.43   600.9 2284.94     608 2286.28   615.3 2288.04   674.3 2305.95
   726.2 2323.16   753.9  2333.4   807.4 2355.14   822.1 2360.64   852.1 2370.67
#Mann= 3 , 0 , 0
       0      .1       0   403.8    .045       0   418.8     .08       0
Bank Sta=403.8,418.8
XS Rating Curve= 0 ,0
Exp/Cntr=0.3,0.1

Type RM Length L Ch R = 1 ,36570.3 ,300,289.2,278.4
XS GIS Cut Line= 4
     1868937.737       153588.14     1868735.188      153729.884
     1868469.007      153881.276     1868219.449      154074.936
#Sta/Elev= 30
     4.7 2445.01    15.6 2442.45    29.4 2438.27    54.1 2429.36    78.8 2419.06
   102.7 2407.74   115.8 2402.47   152.8 2392.02   165.2 2387.29   177.5  2381.6
   197.2 2371.33   255.4 2339.06   314.8 2306.67   359.3  2283.4   367.7 2278.46
   381.5  2269.6     389 2266.95   395.1 2266.44   402.6 2266.22   410.1 2266.49
   466.8 2267.88   515.1 2269.84     618 2277.53   630.8 2278.95   648.9 2283.56
   728.1 2309.31   761.2  2318.3   775.7 2320.85   830.4 2326.37   869.3 2331.37
#Mann= 3 , 0 , 0
       0     .08       0   395.1    .045       0   410.1     .08       0
Bank Sta=395.1,410.1
XS Rating Curve= 0 ,0
Exp/Cntr=0.3,0.1

Type RM Length L Ch R = 1 ,36281.1 ,402.5,403.6,404.9
XS GIS Cut Line= 3
     1868542.121      153246.639     1868405.992      153584.737
     1868132.251      154004.022
#Sta/Elev= 30
     4.7 2376.92    34.4 2371.18    61.4 2368.35      93 2366.59   136.6 2366.75
     169  2358.7   223.8 2339.43   385.8 2273.25   407.7 2260.98     415 2257.87
   418.6 2257.48   426.1 2256.81   433.6 2257.06   490.5 2260.35   498.6 2262.26
   531.9 2276.16   539.2 2277.66   546.9 2277.46     583 2271.57   590.4 2272.13
   597.7 2274.98   619.6 2288.69   626.9 2291.79     657 2297.17   691.9 2301.09
   712.5 2302.21   765.8 2300.11   788.5 2303.11   836.8 2312.66   865.2 2316.35
#Mann= 3 , 0 , 0
     4.7     .08       0   418.6    .045       0   433.6     .08       0
#XS Ineff= 2 , 0
                          447.98         2267.36
Permanent Ineff=
       F       F
Bank Sta=418.6,433.6
XS Rating Curve= 0 ,0
Exp/Cntr=0.3,0.1

Type RM Length L Ch R = 1 ,35877.5 ,160.6,160.2,159.7
XS GIS Cut Line= 4
     1868211.772      153157.867     1868089.902      153458.369
     1868016.424      153573.179     1867824.238      153892.773
#Sta/Elev= 30
     3.3 2359.33    22.6 2357.25    36.1 2354.92      77 2344.33   134.3 2325.75
   193.5 2304.03   224.5 2292.12   276.2 2274.47   312.5 2265.95   343.4 2256.19
   355.4 2252.87   367.4 2250.42   391.5 2247.05   403.5 2243.33     408 2242.53
   415.5  2241.8     423 2242.19   427.5 2242.78   449.9 2249.05     486 2257.64
   498.9 2259.67   523.5 2261.39   567.8 2260.09   589.9 2262.11   604.6 2265.59
   616.9 2271.15   699.5 2318.47   766.8 2354.66   805.8  2378.4   833.5  2396.3
#Mann= 3 , 0 , 0
       0     .08       0     408    .045       0     423     .08       0
Bank Sta=408,423
XS Rating Curve= 0 ,0
Exp/Cntr=0.3,0.1

Type RM Length L Ch R = 1 ,35717.3 ,291.2,295.1,299
XS GIS Cut Line= 4
     1868141.949      153172.112     1867962.847       153361.93
     1867863.345      153531.847     1867754.659      153830.351
#Sta/Elev= 30
     4.3 2371.08    39.9 2361.64    75.9 2350.14   109.8 2338.32   137.6 2326.64
   157.8  2317.3   187.3    2302   266.7 2257.46   285.9 2247.76   298.9 2242.12
   313.7 2239.35   360.5 2237.24     368 2237.19   375.5 2237.84   403.1 2242.94
   414.9 2244.47     450 2247.24   515.3  2257.1     526 2259.49   569.1 2272.81
   580.2 2277.12   622.9 2298.09   655.2 2312.13     666 2317.81   676.7 2324.53
   687.5 2329.79     709 2338.36   719.8 2343.62   752.1 2361.93   775.6 2377.24
#Mann= 3 , 0 , 0
     4.3      .1       0   360.5    .045       0   375.5      .1       0
#XS Ineff= 2 , 0
           318.8 2257.26
Permanent Ineff=
       F       F
Bank Sta=360.5,375.5
XS Rating Curve= 0 ,0
Exp/Cntr=0.3,0.1

Type RM Length L Ch R = 1 ,35422.2 ,388,392.1,394.6
XS GIS Cut Line= 4
     1867840.464      152954.041     1867773.818      153166.874
     1867638.046      153326.902     1867409.202      153663.855
#Sta/Elev= 30
     4.8 2361.64    36.6 2343.69    54.8 2334.04      79 2322.08    98.2 2313.14
   191.6 2272.53     223 2259.53   278.5 2233.22   281.6  2231.9   290.4 2228.95
   294.4 2228.26   301.9 2227.87   309.4 2227.91   414.2 2229.11   443.7 2234.57
   525.7 2247.66   560.2 2254.42   574.6 2256.67   592.9 2258.87   612.1 2261.63
   623.5 2264.59   635.8 2268.28     648 2272.28     665 2278.81   676.7 2284.21
   705.8 2298.47   745.8 2317.11   806.9 2346.33   822.3 2353.56   840.2 2361.45
#Mann= 3 , 0 , 0
       0      .1       0   294.4    .045       0   309.4      .1       0
Bank Sta=294.4,309.4
XS Rating Curve= 0 ,0
Exp/Cntr=0.3,0.1

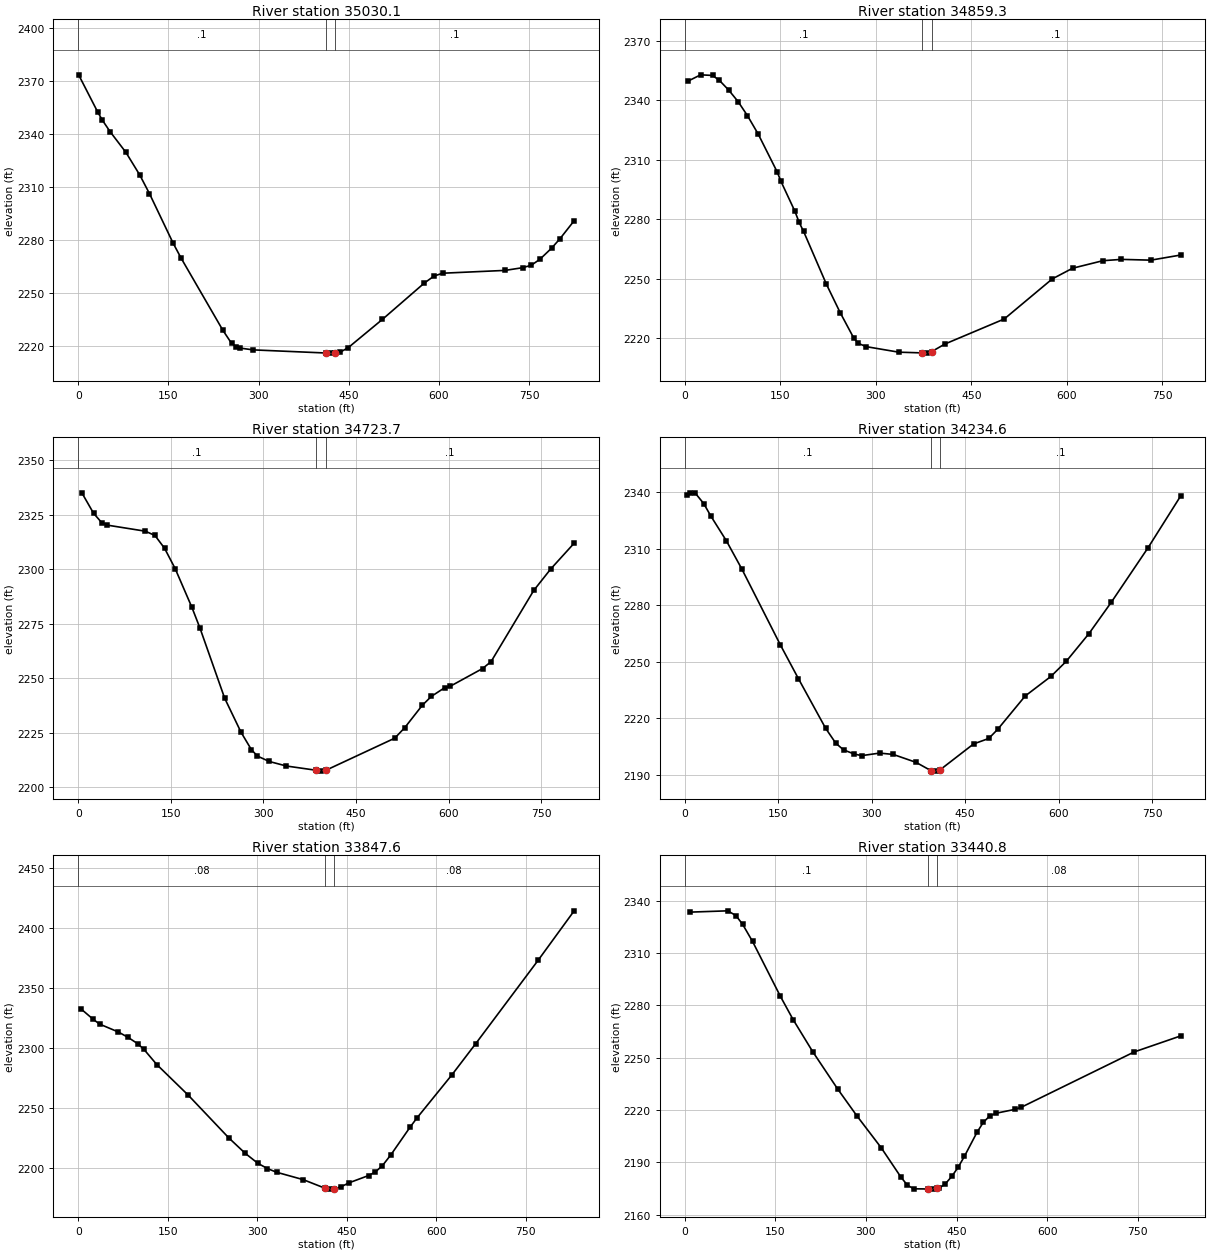
Type RM Length L Ch R = 1 ,35030.1 ,172,170.8,171.2
XS GIS Cut Line= 3
     1867680.151      152792.425     1867358.316      153057.309
     1867066.084      153342.325
#Sta/Elev= 30
      .7 2373.43    32.2 2352.52      40 2347.85    53.1 2341.23    79.3 2329.56
   102.4 2316.73   118.5 2306.21   157.9 2278.14     171 2269.77   240.6 2228.85
     255 2221.48   262.7 2219.51   269.4 2218.75   290.9 2217.74   412.6 2215.96
   420.1  2215.9   427.6 2215.97   434.8 2216.27   448.9 2218.92   506.1 2235.02
   575.6 2255.52   591.9 2259.53   606.2 2261.13   710.1 2262.73   739.1 2264.25
   753.6 2265.62     768 2269.02   787.5 2275.32   801.6 2280.73     825 2290.84
#Mann= 3 , 0 , 0
       0      .1       0   412.6    .045       0   427.6      .1       0
Bank Sta=412.6,427.6
XS Rating Curve= 0 ,0
Exp/Cntr=0.3,0.1

Type RM Length L Ch R = 1 ,34859.3 ,138.7,135.6,132.6
XS GIS Cut Line= 4
     1867552.269      152648.057     1867328.322      152860.616
     1867233.429      152947.918     1866988.606       153185.15
#Sta/Elev= 30
     5.7 2349.68      25 2352.78    43.7 2352.47    54.4 2350.01    69.1 2345.09
    83.8  2339.3    98.5 2332.22   115.3 2322.96   145.2 2303.82   151.1 2299.07
   173.1  2283.9   179.7 2278.35   186.7 2273.78   222.6 2247.09   244.1 2232.84
   265.5 2219.96   272.7 2217.33   284.6 2215.68   336.1 2212.87   372.6 2212.51
   380.1 2212.39   387.6 2213.13   408.7    2217   501.7 2229.61     577 2249.81
     609 2255.22   656.6 2259.02   685.7 2259.68   731.9 2259.29   778.6 2261.87
#Mann= 3 , 0 , 0
       0      .1       0   372.6    .045       0   387.6      .1       0
Bank Sta=372.6,387.6
XS Rating Curve= 0 ,0
Exp/Cntr=0.3,0.1

Type RM Length L Ch R = 1 ,34723.7 ,482.5,489.2,495.8
XS GIS Cut Line= 3
     1867475.954      152554.439      1867253.55      152743.483
     1866905.115      153117.865
#Sta/Elev= 30
     5.9 2335.02    24.8 2325.67      38 2321.37    46.2 2320.25   108.7 2317.43
   124.3 2315.47   139.9 2309.58   157.1 2300.23   184.1 2282.55   197.3 2272.95
   237.2 2240.88   263.7 2225.27   280.5 2217.29   290.3 2214.34   309.4 2211.87
   337.1 2209.79   385.6 2207.83   393.1 2207.44   400.6 2207.76   512.8 2222.56
   529.1 2227.43   557.3 2237.61     572  2241.7   593.5 2245.67   601.9 2246.24
   654.9 2254.46   668.7 2257.63   737.8 2290.25   765.4 2300.12   803.3 2311.93
#Mann= 3 , 0 , 0
       0      .1       0   385.6    .045       0   400.6      .1       0
Bank Sta=385.6,400.6
XS Rating Curve= 0 ,0
Exp/Cntr=0.3,0.1

Type RM Length L Ch R = 1 ,34234.6 ,382.7,387,391.3
XS GIS Cut Line= 4
      1867197.37      152281.771      1866941.16      152469.658
      1866793.09       152568.29     1866628.014      152818.864
#Sta/Elev= 30
     4.1 2338.56       9 2339.52    16.6 2339.56    30.7  2333.8    41.7 2327.39
    66.8 2314.19    91.9 2299.05   153.7 2258.83   182.6 2240.97   226.1 2214.75
   242.4 2206.84   254.9 2203.28   272.2 2201.07     284 2200.23   312.9 2201.59
   334.7 2200.86   371.2 2196.67   395.2 2192.27   402.7 2192.02   410.2 2192.82
   463.5 2206.43   487.8 2209.32   502.2 2214.17   546.3 2231.84   587.6 2242.23
   612.1  2250.2   648.6 2264.91   684.5 2281.56   743.5 2310.47   795.7 2337.85
#Mann= 3 , 0 , 0
       0      .1       0   395.2    .045       0   410.2      .1       0
Bank Sta=395.2,410.2
XS Rating Curve= 0 ,0
Exp/Cntr=0.3,0.1

Type RM Length L Ch R = 1 ,33847.6 ,403.7,406.8,410.7
XS GIS Cut Line= 4
     1867076.616      152068.892     1866765.698      152167.077
     1866609.035      152234.324     1866318.663      152401.336
#Sta/Elev= 30
     4.1 2332.95    25.3 2323.98    35.9 2320.07    67.3  2313.5    83.4 2309.07
    99.5 2303.84   110.2 2299.02   131.8 2286.39   184.4 2260.97   252.7 2225.26
   279.9 2212.58     301  2204.3   317.2 2199.83   332.6 2196.78   377.2 2190.63
   413.7  2183.5   421.2 2182.73   428.7 2182.92   440.8 2184.71   454.3 2188.03
     487 2194.07   498.4 2197.13   510.1 2202.31   524.4  2211.4   556.7  2234.5
   568.4 2242.24   626.8    2278   666.5 2303.82     771 2373.12   831.5 2414.34
#Mann= 3 , 0 , 0
       0     .08       0   413.7    .045       0   428.7     .08       0
Bank Sta=413.7,428.7
XS Rating Curve= 0 ,0
Exp/Cntr=0.3,0.1

Type RM Length L Ch R = 1 ,33440.8 ,215,212,208.2
XS GIS Cut Line= 3
     1866941.881       151728.21     1866546.795      151840.277
     1866148.604      151938.138
#Sta/Elev= 30
     9.1 2333.46    71.3  2334.2    84.8 2331.48    95.9 2326.46   112.3 2316.65
   158.4 2285.17   179.4 2271.86   211.7 2253.55     253 2232.14   284.6 2216.84
   325.2 2198.38     358 2181.47   368.7 2176.85   379.2 2174.83   403.2 2174.74
   410.7 2174.65   418.2 2175.09   421.2 2175.16   431.6 2177.78     442 2181.95
   452.4 2187.09   462.8 2193.37   483.7 2207.19   494.1 2212.89   504.5 2216.51
   514.9 2218.13   546.1 2220.34   556.6 2221.52   744.1 2253.33   820.7 2262.47
#Mann= 3 , 0 , 0
       0      .1       0   403.2    .045       0   418.2     .08       0
Bank Sta=403.2,418.2
XS Rating Curve= 0 ,0
Exp/Cntr=0.3,0.1

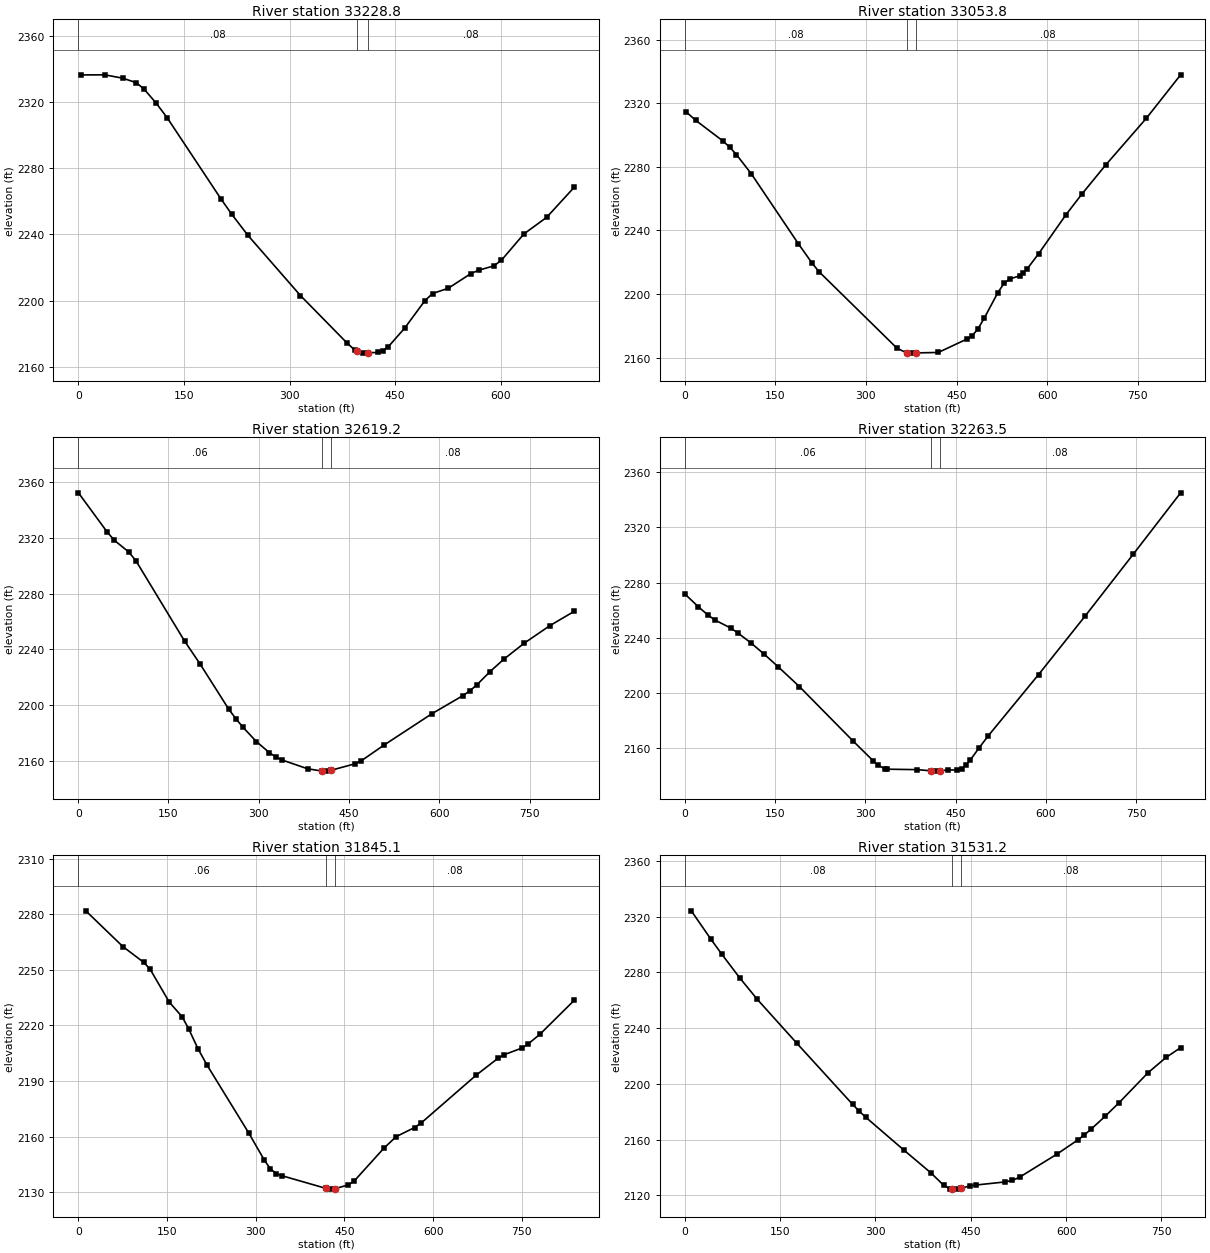
Type RM Length L Ch R = 1 ,33228.8 ,174.5,175,175.5
XS GIS Cut Line= 4
     1866854.101      151470.042     1866544.881      151610.874
     1866371.902      151685.883     1866206.577      151745.584
#Sta/Elev= 30
     4.2 2336.39    37.6 2336.45    63.1 2334.43    82.1 2331.76    93.2 2327.98
   111.1 2319.14   126.6 2310.32   202.8 2261.39     218  2252.2     241 2239.43
   315.5 2203.11   381.9  2174.3   392.9 2170.06   396.4  2169.4   403.9  2168.3
   411.4 2168.56     426 2168.68   432.5 2169.65   440.2 2172.14   463.3 2183.31
   492.1 2199.93   503.1 2204.32   525.2 2207.45   557.5 2216.37   568.3 2218.36
   589.8 2220.98   600.6  2224.3   632.8 2240.32   665.1 2250.36   704.1 2268.47
#Mann= 3 , 0 , 0
       0     .08       0   396.4    .045       0   411.4     .08       0
Bank Sta=396.4,411.4
XS Rating Curve= 0 ,0
Exp/Cntr=0.3,0.1

Type RM Length L Ch R = 1 ,33053.8 ,434.3,434.6,435
XS GIS Cut Line= 4
     1866764.459       151311.53     1866546.412      151424.118
     1866306.078      151522.088     1866007.828      151626.733
#Sta/Elev= 30
     2.7 2314.42    18.4 2309.14    62.9 2296.32    74.3 2292.39    85.7 2287.64
   110.4 2275.51   188.1 2231.63   210.9 2219.41   222.3 2214.05   351.5 2165.89
   367.8 2162.89   375.3  2162.8   382.8 2162.94   419.8 2163.21   467.9 2171.77
   475.7 2173.66   485.4 2177.97   496.3 2185.05   517.9 2200.48   528.6 2206.71
   538.5  2209.5   554.4 2211.35   560.8 2213.08   566.6 2215.57   586.1  2225.4
     631 2249.73   657.2 2262.66   697.2 2281.22   764.4 2310.55     821 2337.81
#Mann= 3 , 0 , 0
       0     .08       0   367.8    .045       0   382.8     .08       0
Bank Sta=367.8,382.8
XS Rating Curve= 0 ,0
Exp/Cntr=0.3,0.1

Type RM Length L Ch R = 1 ,32619.2 ,359.4,355.7,352
XS GIS Cut Line= 4
      1866638.63      150885.298     1866402.079      151029.988
     1866200.454      151111.837     1865905.924       151259.48
#Sta/Elev= 30
      .4 2352.54    48.4 2324.24    60.3 2318.34      84 2310.06    95.9 2303.74
     177  2245.9   202.6 2229.54     250 2197.23   261.9 2190.32   273.7  2184.2
   296.2 2173.82   317.7 2165.89   328.6 2162.75   339.5 2160.53   381.1 2154.33
   404.7 2152.71   412.2 2152.63   419.7 2153.18   459.6 2157.85   470.5 2160.08
   507.9 2171.24   587.9 2193.89   639.3 2206.87   650.7 2210.24     662 2214.39
   684.6 2224.19   707.2 2232.98   741.2 2244.54   783.9 2257.14   824.2 2267.38
#Mann= 3 , 0 , 0
       0     .06       0   404.7    .045       0   419.7     .08       0
Bank Sta=404.7,419.7
XS Rating Curve= 0 ,0
Exp/Cntr=0.3,0.1

Type RM Length L Ch R = 1 ,32263.5 ,405.5,418.4,431.2
XS GIS Cut Line= 4
     1866476.709      150597.553       1866217.8       150701.32
     1866016.759      150824.049     1865737.689      150956.723
#Sta/Elev= 30
      .8 2271.57    22.6 2262.51    38.6 2256.49    50.6 2252.79    77.1  2246.9
      88 2243.59   109.8 2236.36   131.6 2228.27   154.9 2219.11   190.6 2204.57
   278.9 2165.43   313.1 2150.74   320.2 2147.94     332 2145.01   335.2 2144.72
     386 2144.37   408.6 2143.56     415  2143.3   423.6 2143.63   437.4 2144.13
   452.9 2144.11   460.3 2145.18   467.6 2147.93   474.2  2151.3   488.3 2159.83
   504.4 2169.08   587.6 2213.32   665.1 2255.83   744.7 2300.51   823.5 2345.11
#Mann= 3 , 0 , 0
       0     .06       0   408.6    .045       0   423.6     .08       0
Bank Sta=408.6,423.6
XS Rating Curve= 0 ,0
Exp/Cntr=0.3,0.1

Type RM Length L Ch R = 1 ,31845.1 ,317,313.9,310.7
XS GIS Cut Line= 4
     1866467.673      150477.372     1866197.392      150372.466
     1865934.096      150367.873      1865649.08       150356.68
#Sta/Elev= 30
    12.8 2281.82    75.4 2262.56   110.5 2254.06   121.4  2250.4   153.9 2232.56
   175.6 2224.68   186.5 2218.29   202.3 2207.51   217.9  2198.5   288.3 2161.92
   314.9 2147.14     325 2142.52   335.1 2139.96   345.2 2138.77   418.6 2132.04
   426.1 2131.61   433.6 2131.82   456.5 2133.87   466.4 2135.91   516.5  2153.6
   537.4 2159.91   568.7 2164.85   580.2  2167.4   673.1 2193.19   709.5 2202.17
   719.6  2204.1     750 2207.73   760.1 2209.83   780.3 2215.09   838.5 2233.48
#Mann= 3 , 0 , 0
       0     .06       0   418.6    .045       0   433.6     .08       0
Bank Sta=418.6,433.6
XS Rating Curve= 0 ,0
Exp/Cntr=0.3,0.1

Type RM Length L Ch R = 1 ,31531.2 ,463.2,449.8,436.5
XS GIS Cut Line= 4
     1866517.327      150077.023     1866208.108         150051.
     1866013.697      150077.023     1865758.056      150174.994
#Sta/Elev= 30
    10.4 2324.14    41.5 2303.62    58.2 2293.15    86.3 2276.23   114.3 2260.61
   176.6 2229.08   264.1 2185.37     275 2180.24   285.2 2175.96   344.9 2152.52
   387.1  2136.3   407.5 2127.26   417.7 2124.59   420.4 2124.57   427.9 2124.54
   435.4 2125.33   448.3 2126.74   458.5  2127.5     504 2129.69   515.7 2130.82
   526.9 2133.11   585.6 2149.64   618.1 2159.68   628.9 2163.45   639.7 2167.68
   661.4 2176.76   683.1 2186.38   729.2 2208.14   757.5 2219.05   780.2 2226.01
#Mann= 3 , 0 , 0
       0     .08       0   420.4    .045       0   435.4     .08       0
Bank Sta=420.4,435.4
XS Rating Curve= 0 ,0
Exp/Cntr=0.3,0.1

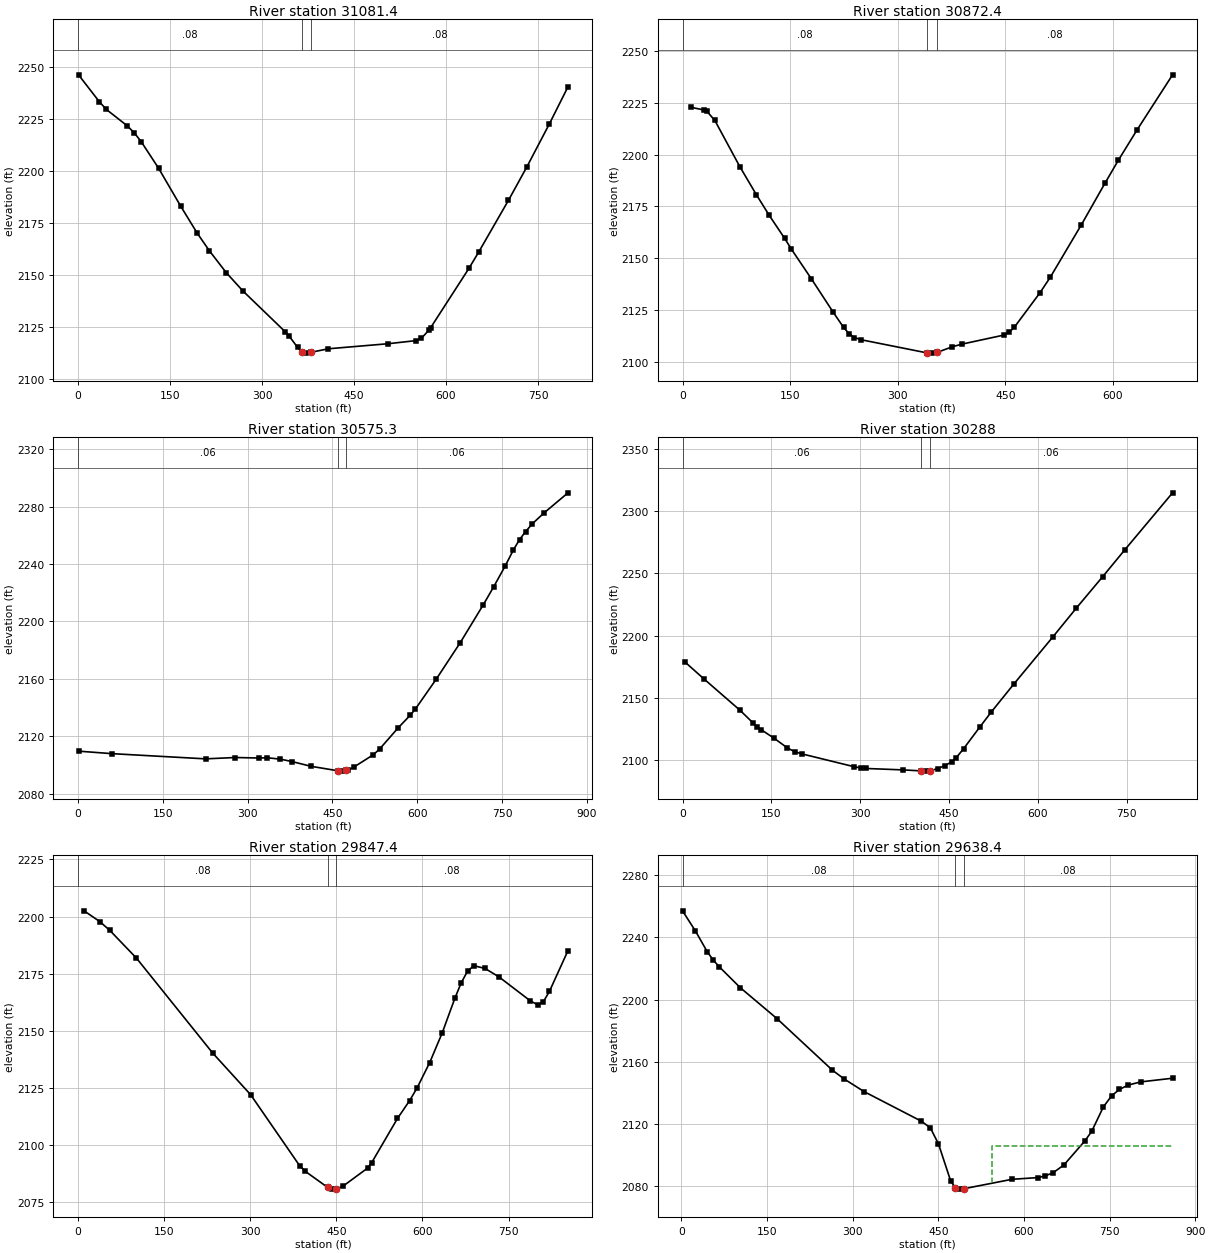
Type RM Length L Ch R = 1 ,31081.4 ,211.3,209,205.7
XS GIS Cut Line= 4
     1866284.647      149444.807     1866082.957       149547.65
     1865888.173      149715.757     1865641.234      149911.395
#Sta/Elev= 30
       1 2246.02    35.1 2233.03    46.4 2229.39    80.5 2221.52    91.9 2218.14
   103.2 2213.92   131.4 2201.21   167.8 2182.83     194 2170.21   214.1 2161.62
   241.8 2151.05   268.5 2142.39   338.1 2122.61   343.8  2120.8   358.1 2115.15
     365 2113.17   372.5 2112.43     380 2112.84   408.3 2114.52   505.4 2116.94
   550.2 2118.41   559.7 2119.52   572.7 2123.67   574.9 2124.64   637.2 2153.08
   653.7 2161.21   701.7 2185.79     732    2202     768 2222.25   798.7 2240.27
#Mann= 3 , 0 , 0
       0     .08       0     365    .045       0     380     .08       0
Bank Sta=365,380
XS Rating Curve= 0 ,0
Exp/Cntr=0.3,0.1

Type RM Length L Ch R = 1 ,30872.4 ,304.2,297.1,290.6
XS GIS Cut Line= 4
     1866111.668      149326.937      1865883.58      149447.869
     1865751.932      149584.109     1865566.707      149729.534
#Sta/Elev= 30
    11.3 2222.89    30.1 2221.56    34.2 2220.83    45.1  2216.5      80 2194.14
   102.9 2180.69   120.7 2170.78   142.3  2159.6   151.9 2154.29   179.8 2139.94
   209.7 2124.07   224.6 2116.54   232.1 2113.55   239.6 2111.68   248.9 2110.61
   340.2  2104.3   347.7 2104.14   355.2 2104.54   376.3 2107.22     389 2108.45
   447.6 2112.83   455.1 2114.18   462.3 2116.52   498.3  2133.3   512.7 2140.81
     556 2166.13   588.7 2186.09   607.4 2197.21   633.1 2211.67   683.1 2238.54
#Mann= 3 , 0 , 0
       0     .08       0   340.2    .045       0   355.2     .08       0
Bank Sta=340.2,355.2
XS Rating Curve= 0 ,0
Exp/Cntr=0.3,0.1

Type RM Length L Ch R = 1 ,30575.3 ,284.4,287.3,290.2
XS GIS Cut Line= 4
     1865932.998      149022.521     1865661.616      149192.227
     1865563.645      149418.784     1865463.502      149701.364
#Sta/Elev= 30
     2.5 2109.51    59.7 2107.82   225.7 2104.18   278.3 2105.12   320.1 2104.76
     335 2104.95   358.2 2103.96   379.1 2102.25   412.1 2098.99   459.7 2095.88
   467.2 2095.62   474.7 2096.16   478.3 2096.35   488.2 2098.49   522.3 2107.01
   533.4 2110.96   566.4 2125.82   587.9 2134.68   596.8 2138.92     634 2159.94
     676 2185.12   716.7 2211.52   735.6 2224.39   755.2  2238.4   770.3 2249.99
   781.1 2257.17   791.8 2262.73   803.4 2268.06     824  2275.6   866.7 2289.74
#Mann= 3 , 0 , 0
       0     .06       0   459.7    .045       0   474.7     .06       0
Bank Sta=459.7,474.7
XS Rating Curve= 0 ,0
Exp/Cntr=0.3,0.1

Type RM Length L Ch R = 1 ,30288   ,432.2,440.6,448.9
XS GIS Cut Line= 4
     1865582.829      148874.419     1865422.813      149078.949
     1865298.452      149287.805     1865136.519      149569.425
#Sta/Elev= 30
     3.9 2178.82      36 2165.24    97.1 2139.98   118.7 2130.01   126.5 2126.58
   133.2 2124.26   154.8 2117.48   176.9  2109.8   189.7 2106.65   202.6 2104.83
   289.7 2094.66   301.5 2093.61   309.6 2093.24   372.2 2092.09     403 2091.29
   410.5  2091.1     418 2091.35     431 2093.15   442.8  2095.5   454.6 2098.52
   462.2 2101.83   474.9 2109.23   501.6 2126.19   521.3 2138.49     560 2161.29
     625 2198.61     665 2221.97   709.5 2247.21   746.7 2268.67   827.6 2314.58
#Mann= 3 , 0 , 0
       0     .06       0     403    .045       0     418     .06       0
Bank Sta=403,418
XS Rating Curve= 0 ,0
Exp/Cntr=0.3,0.1

Type RM Length L Ch R = 1 ,29847.4 ,213.2,209,204.9
XS GIS Cut Line= 4
     1865502.414      148795.753     1865202.092      148779.249
     1865000.315      148936.585     1864726.411      149051.386
#Sta/Elev= 30
    10.7 2202.51    38.1  2197.8    55.4 2193.99   101.9 2181.83   234.7 2140.29
   300.8 2122.06     386 2091.05   396.3 2088.46   435.2 2081.46   442.7 2080.73
   450.2  2080.9   461.1  2081.9   504.4 2089.91   511.6 2092.28   556.6 2111.65
   577.9 2119.51   590.8 2125.03   612.8 2136.13   634.7 2149.21   656.6 2164.26
   667.6 2170.99   678.6 2176.08   689.6  2178.5   709.2 2177.29   733.4 2173.59
   788.3 2163.06   800.8 2161.41   810.2 2162.52   821.2 2167.21   853.6 2185.09
#Mann= 3 , 0 , 0
       0     .08       0   435.2    .045       0   450.2     .08       0
Bank Sta=435.2,450.2
XS Rating Curve= 0 ,0
Exp/Cntr=0.3,0.1

Type RM Length L Ch R = 1 ,29638.4 ,159.3,160.9,162.5
XS GIS Cut Line= 4
     1865437.451      148507.534     1865066.235      148601.295
     1864913.156      148775.422     1864777.298      148980.165
#Sta/Elev= 30
     1.8 2257.11    24.4 2244.18    45.2 2230.76    55.7  2225.4    66.1 2221.15
   103.1 2207.65   167.1 2187.84   264.3 2154.64   285.2 2148.91   320.2 2140.77
   420.2 2121.81     436 2117.53   450.3 2107.16   471.8 2083.17   480.1 2078.96
   487.6 2078.09   495.1 2078.38   579.3 2084.42   623.9 2085.49   637.1 2086.53
   651.7 2088.78   670.1 2093.64   706.5    2109   718.6 2115.16   739.2    2131
   753.8 2138.17   767.2 2142.21     783 2145.07   804.9 2147.09   860.4 2149.43
#Mann= 3 , 0 , 0
     1.8     .08       0   480.1    .045       0   495.1     .08       0
#XS Ineff= 2 , 0
                          544.76         2105.66
Permanent Ineff=
       F       F
Bank Sta=480.1,495.1
XS Rating Curve= 0 ,0
Exp/Cntr=0.3,0.1