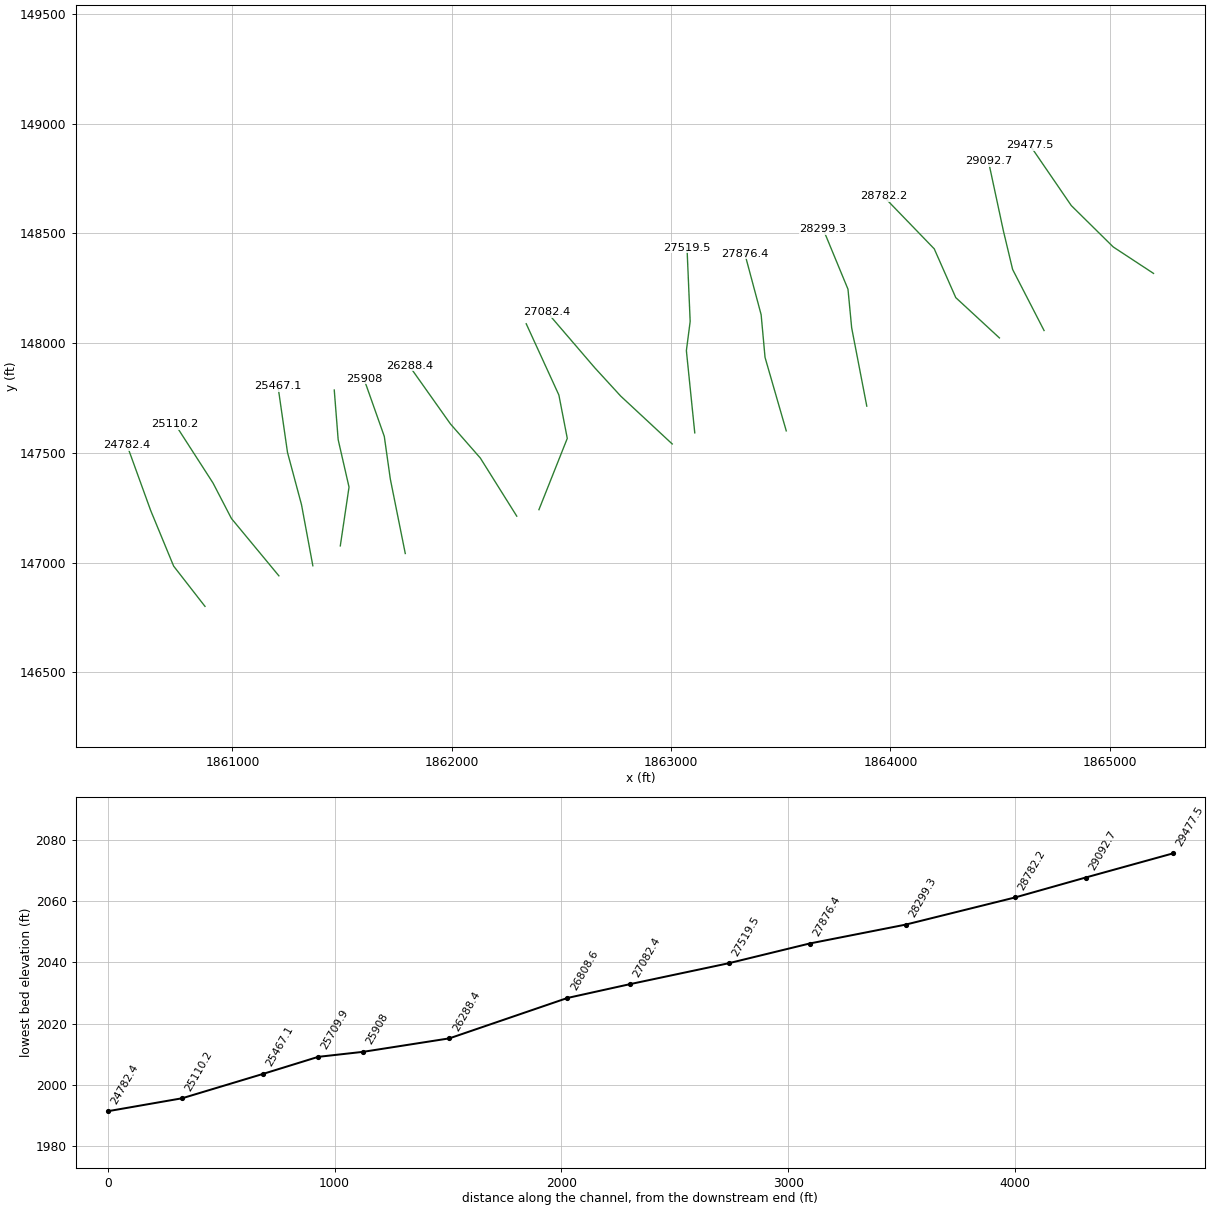
HEC-RAS study North Fork Elkhorn.prj: NFElkhorn

--- North Fork Elkhorn.g01 (geometry) --- (continued)

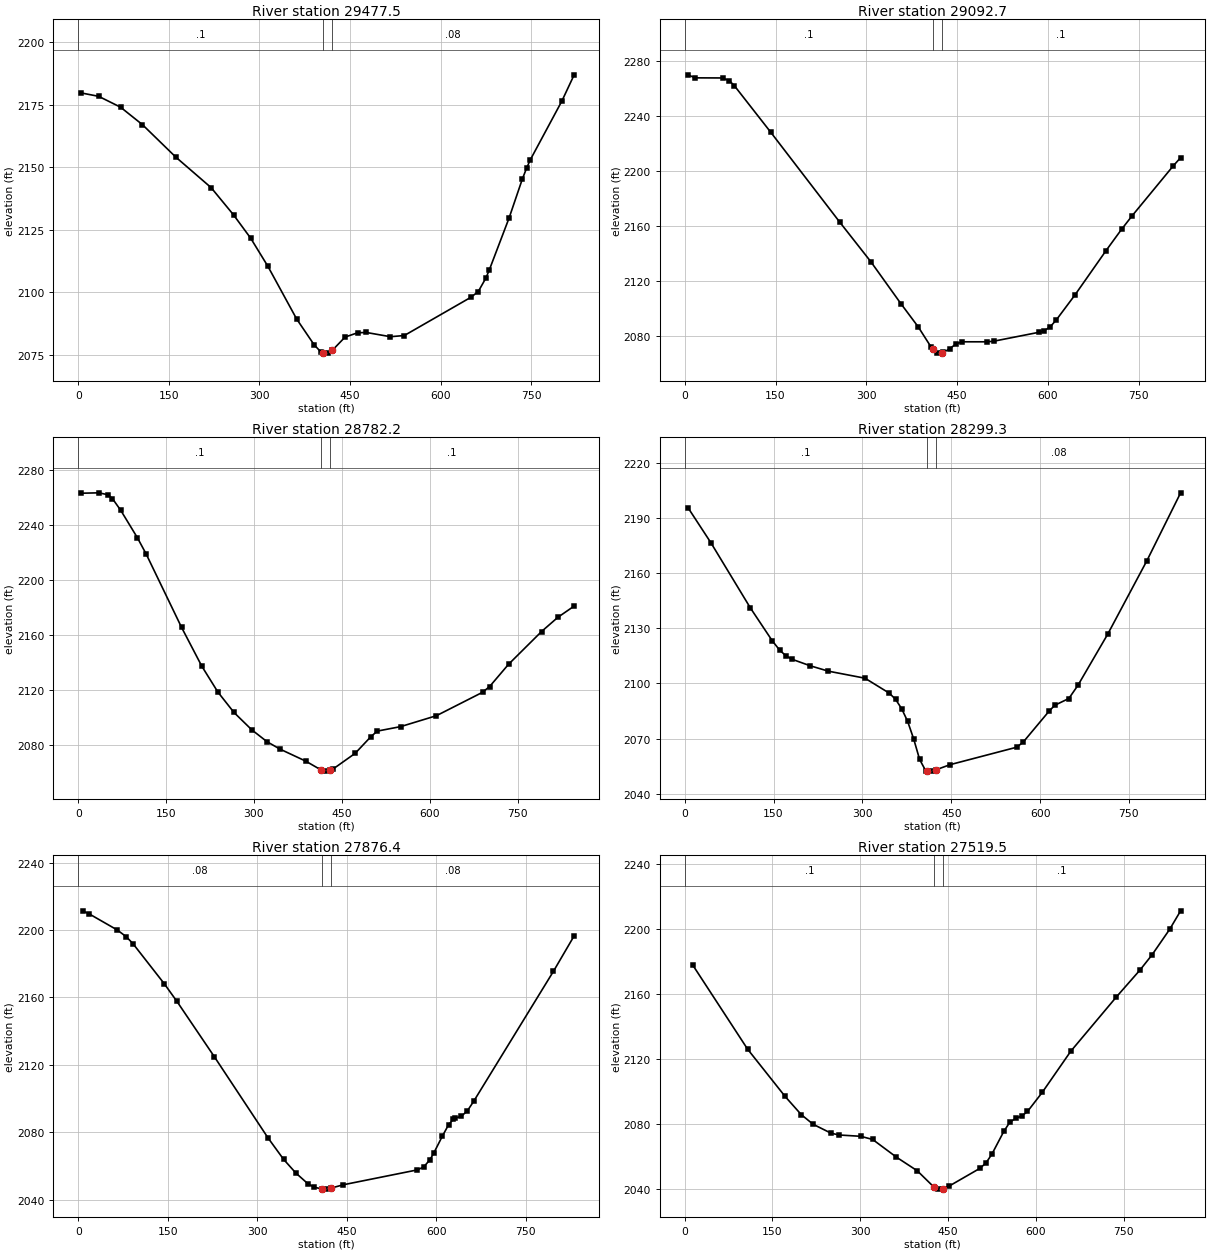
Type RM Length L Ch R = 1 ,29477.5 ,397.5,384.8,372.1
XS GIS Cut Line= 4
     1865199.318      148318.146     1865015.378      148438.871
     1864824.274      148627.366     1864636.277      148901.682
#Sta/Elev= 30
     4.1 2179.76    33.8 2178.37    70.1 2174.02   106.4 2167.01   161.6 2154.03
     220 2141.83   257.1 2130.93   285.5 2121.59   313.9 2110.38   361.6 2089.25
   390.5 2078.95     402 2075.98   405.8 2075.68   413.3 2075.59   420.8 2076.75
   441.8 2082.02   462.5 2083.73   476.9 2083.86   516.9 2082.16   539.9 2082.64
   650.3 2097.97   662.3 2100.25   674.8  2105.6   680.2 2108.67   713.4 2129.75
   735.2 2145.25   742.5 2149.75   748.4 2152.95   800.7 2176.49     821 2186.97
#Mann= 3 , 0 , 0
       0      .1       0   405.8    .045       0   420.8     .08       0
Bank Sta=405.8,420.8
XS Rating Curve= 0 ,0
Exp/Cntr=0.3,0.1

Type RM Length L Ch R = 1 ,29092.7 ,306.4,310.5,314.6
XS GIS Cut Line= 4
      1864700.28      148057.912     1864557.003       148335.97
     1864515.055      148511.026     1864446.597      148829.998
#Sta/Elev= 30
     5.6 2270.15      17 2267.95    62.5 2267.87    73.9 2265.84    82.2 2262.16
   142.2 2228.34     256 2163.04   307.5 2134.17   357.2 2103.61   385.7  2086.8
   406.5 2072.42   409.4 2071.06   416.9 2067.71   424.4 2068.03   427.3 2068.26
   437.7  2070.9   448.1 2074.44   457.9 2075.95   499.8 2075.95   510.4 2076.39
   585.2 2082.88   593.2 2083.84   603.5 2086.79   613.8 2091.92   644.4 2109.95
   695.9 2142.32   721.5 2157.78   738.5 2167.38   806.6  2203.8     819 2209.92
#Mann= 3 , 0 , 0
       0      .1       0   409.4    .045       0   424.4      .1       0
Bank Sta=409.4,424.4
XS Rating Curve= 0 ,0
Exp/Cntr=0.3,0.1

Type RM Length L Ch R = 1 ,28782.2 ,490.2,483,475.8
XS GIS Cut Line= 4
     1864496.685      148024.235     1864297.683       148207.93
     1864199.712      148429.894     1863968.223      148669.295
#Sta/Elev= 30
     4.5  2262.8    35.2 2263.09    51.2 2261.67    58.4 2258.91    72.7 2250.32
   100.9  2230.6     116  2218.7   176.3 2165.57     211  2137.3   238.5 2118.51
   265.8 2103.81   296.3 2091.16   322.4 2082.53   344.5 2077.17   388.3 2068.48
   414.4 2062.11   421.9 2061.22   429.4 2061.76   434.4 2062.58   472.7 2074.12
   499.3 2086.11   510.4 2090.25   550.2 2093.49   611.4 2101.42   690.1  2118.4
   702.2 2122.58   734.6 2138.75   790.9  2162.5   818.6 2172.76   846.5 2180.94
#Mann= 3 , 0 , 0
       0      .1       0   414.4    .045       0   429.4      .1       0
Bank Sta=414.4,429.4
XS Rating Curve= 0 ,0
Exp/Cntr=0.3,0.1

Type RM Length L Ch R = 1 ,28299.3 ,423.1,422.9,422.6
XS GIS Cut Line= 4
     1863892.008      147713.472     1863823.138      148070.159
     1863806.299      148246.199     1863692.748      148520.687
#Sta/Elev= 30
     5.6 2195.57      44 2176.64   111.1 2140.97   147.6 2123.32   160.2 2118.17
   170.5 2115.16   180.8 2113.21   211.7 2109.64   242.5 2106.69   304.4 2102.86
   345.6 2094.69   355.9 2091.42   366.2 2086.33   376.3 2079.46   386.5 2069.92
   396.6  2058.7   406.8 2052.57   409.5 2052.41     417 2052.34   424.5 2053.09
     448 2055.85   560.7 2065.36   571.6 2068.17   615.4 2085.04     625 2088.19
   648.5 2091.82   663.7 2098.91     714 2126.73   780.3 2166.77   837.2 2203.65
#Mann= 3 , 0 , 0
       0      .1       0   409.5    .045       0   424.5     .08       0
Bank Sta=409.5,424.5
XS Rating Curve= 0 ,0
Exp/Cntr=0.3,0.1

Type RM Length L Ch R = 1 ,27876.4 ,362.8,356.9,351
XS GIS Cut Line= 4
     1863524.921      147600.644     1863428.194      147935.449
     1863410.387       148130.01      1863336.01      148407.717
#Sta/Elev= 30
     7.4 2211.37    17.9 2209.65    65.8 2199.93    80.6 2195.96    91.6 2191.97
   144.3 2168.08   165.3  2157.7   228.1 2124.83   318.2 2076.58   344.3 2063.86
   364.8 2055.76   385.1 2049.36   395.2 2047.34   408.1 2046.33   415.6 2046.18
   423.1 2046.71   444.3 2048.76   568.7 2057.61   579.1 2059.33   589.6 2063.59
   595.9 2067.47   610.5 2077.66     621 2084.45     629 2087.69   631.5 2088.31
     642 2089.34   652.4 2092.66   662.9 2098.26   796.6 2175.42   831.4 2196.52
#Mann= 3 , 0 , 0
       0     .08       0   408.1    .045       0   423.1     .08       0
Bank Sta=408.1,423.1
XS Rating Curve= 0 ,0
Exp/Cntr=0.3,0.1

Type RM Length L Ch R = 1 ,27519.5 ,417.3,437.1,457
XS GIS Cut Line= 4
     1863107.779      147591.734     1863069.546      147966.332
     1863086.828      148099.244      1863072.37      148435.558
#Sta/Elev= 30
    13.7 2177.84   107.6 2125.92   171.6 2096.83   199.1 2085.67   219.4  2079.7
   249.9 2074.22   263.9 2073.09   300.7 2072.29   321.1 2070.34   361.8 2059.42
   397.4 2051.02   425.6 2041.06   433.1 2039.74   440.6 2039.97   451.6 2041.58
   504.5 2052.58   514.7 2055.88   524.8 2061.28   545.1 2075.26   555.2 2080.84
   565.3 2083.36   575.5 2084.67   585.6 2087.57   610.7 2099.28   659.6 2124.71
   737.5 2158.17   777.9 2174.77   798.2    2184   828.6 2199.87   847.2 2211.21
#Mann= 3 , 0 , 0
       0      .1       0   425.6    .045       0   440.6      .1       0
Bank Sta=425.6,440.6
XS Rating Curve= 0 ,0
Exp/Cntr=0.3,0.1

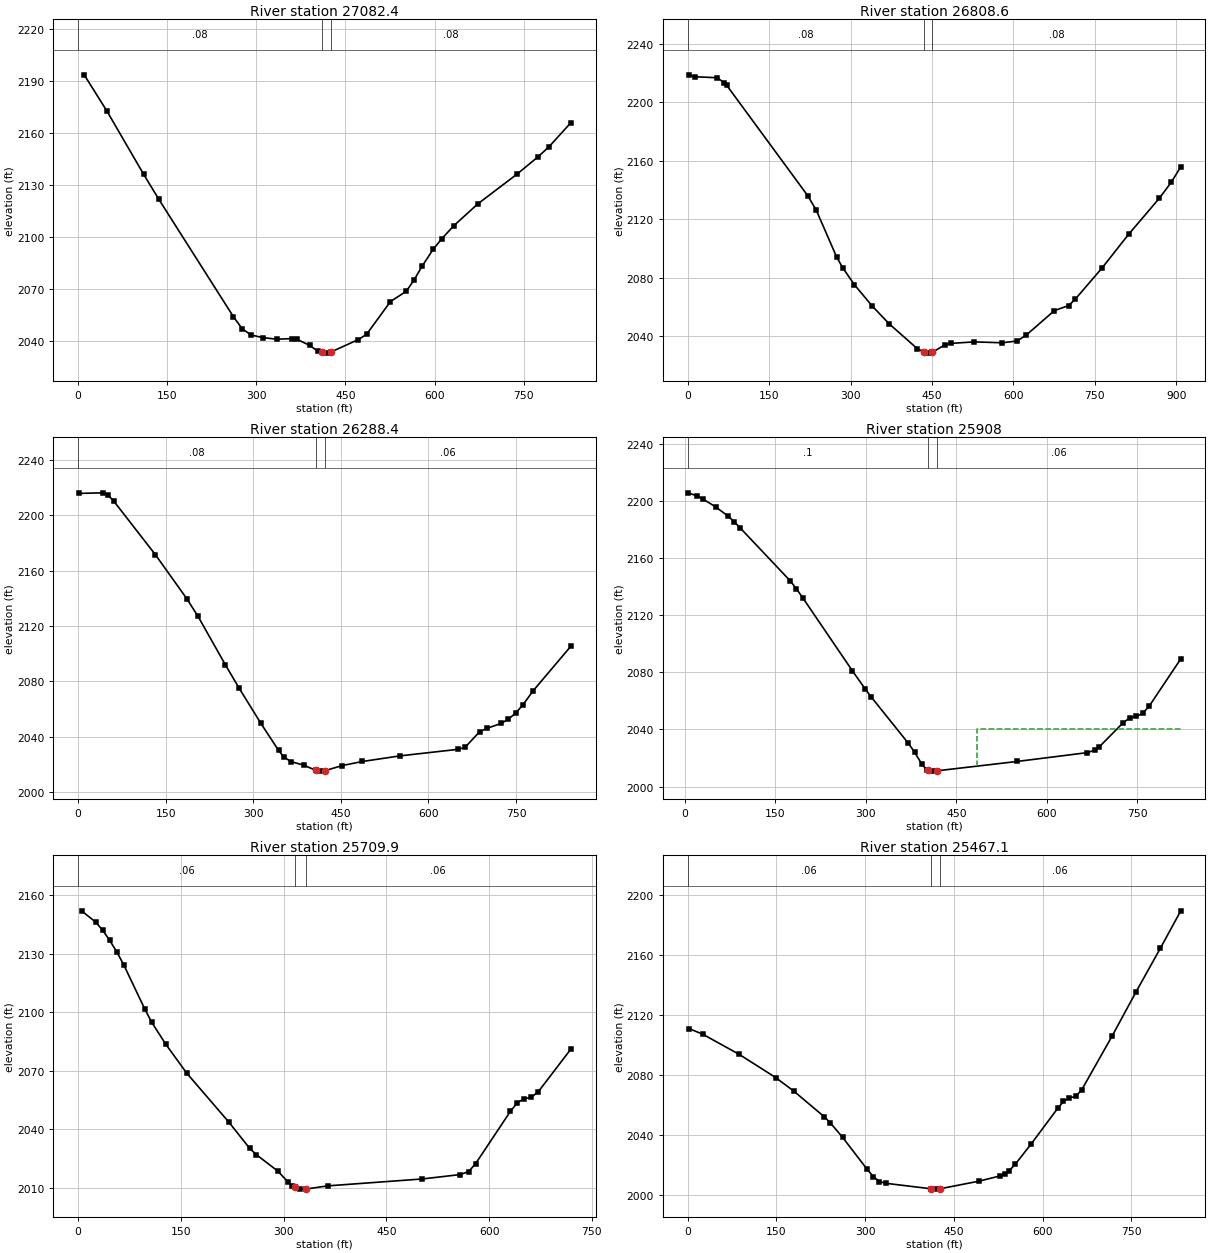
Type RM Length L Ch R = 1 ,27082.4 ,286.3,273.7,261.2
XS GIS Cut Line= 4
     1863004.977      147541.081     1862769.955      147759.408
     1862652.084      147887.995     1862434.207      148141.696
#Sta/Elev= 30
    10.3 2193.36    48.5  2172.5   110.5 2135.91   136.1 2121.47   261.4 2053.91
   276.3 2046.89   291.1 2043.34   310.9 2041.83   334.6  2040.9     360 2041.25
   368.2 2040.88   389.5 2037.39     404 2033.92   410.8 2033.37   418.3 2032.88
   425.8 2033.56   471.8 2040.72   485.5 2043.71   525.8 2062.63   552.5 2068.59
   565.8 2075.28   579.1 2083.08   597.5 2092.69   611.9 2098.77   632.5 2106.39
   672.5 2118.87   739.1  2136.2   774.2 2146.11   792.5 2151.85   829.6 2165.85
#Mann= 3 , 0 , 0
       0     .08       0   410.8    .045       0   425.8     .08       0
Bank Sta=410.8,425.8
XS Rating Curve= 0 ,0
Exp/Cntr=0.3,0.1

Type RM Length L Ch R = 1 ,26808.6 ,508.2,520.2,532.3
XS GIS Cut Line= 4
     1862397.315      147241.646      1862526.56      147566.529
      1862488.29      147764.001      1862339.32      148088.839
#Sta/Elev= 30
     2.1 2218.79      13 2217.48    53.7  2216.8    67.4 2213.41    71.8 2211.55
   221.3 2135.92   236.8 2126.06   274.2 2094.16   285.1 2086.96   306.9 2075.21
   339.6 2060.67     371 2048.44   422.5 2031.54   435.6 2028.89   443.1  2028.4
   450.6 2028.98     474 2034.15   485.6 2035.08   527.7  2036.1   579.2 2035.48
   606.7 2036.68   623.7  2040.8   675.3 2057.47   701.6 2060.95   713.5 2065.16
   763.7 2086.88   812.2 2109.73   868.5 2134.25   890.8 2145.33   908.2 2155.88
#Mann= 3 , 0 , 0
       0     .08       0   435.6    .045       0   450.6     .08       0
Bank Sta=435.6,450.6
XS Rating Curve= 0 ,0
Exp/Cntr=0.3,0.1

Type RM Length L Ch R = 1 ,26288.4 ,393.6,380.4,367.2
XS GIS Cut Line= 4
     1862296.243      147212.191     1862130.002      147477.121
     1861993.845      147632.353     1861805.905      147897.463
#Sta/Elev= 30
     1.2 2215.66    43.2 2216.08    50.6 2214.75      61 2210.18   132.6 2171.33
   186.3 2139.59   205.3 2127.01     252 2092.16   275.9 2075.03   312.8 2049.88
   343.3 2030.21     352 2025.64   364.2 2022.12   386.4 2019.54   407.5 2015.72
     415 2015.22   422.5 2015.52   452.6 2019.26   486.9 2022.17   551.1 2026.22
   650.3 2030.93   662.7 2032.38   687.5 2043.59   699.9 2046.07   724.7 2049.67
   737.1 2052.86   749.5 2057.11   761.9 2063.13   779.7 2073.38   844.2 2105.49
#Mann= 3 , 0 , 0
       0     .08       0   407.5    .045       0   422.5     .06       0
Bank Sta=407.5,422.5
XS Rating Curve= 0 ,0
Exp/Cntr=0.3,0.1

Type RM Length L Ch R = 1 ,25908   ,196.1,198.1,200
XS GIS Cut Line= 4
     1861787.992      147041.914     1861719.798      147381.296
     1861692.279      147575.714     1861598.999      147839.312
#Sta/Elev= 30
     5.1 2205.74      20 2203.71    29.9 2201.46      51 2195.96    71.6 2189.51
    81.9 2185.53    92.2 2181.01   174.8 2144.11   185.1  2138.5   195.4 2132.35
   277.9 2081.06   298.6 2068.67   308.9 2062.84   370.5 2030.38   380.8 2024.21
   392.6 2015.95   401.2 2011.55     403  2011.4   410.5 2010.82     418 2011.04
   550.8 2017.58   667.5 2023.79   679.2 2025.48   687.1 2027.85   726.7 2044.75
   737.4 2048.07   748.2 2049.17   758.9 2051.23   769.6 2056.24   822.1 2089.43
#Mann= 3 , 0 , 0
     5.1      .1       0     403    .045       0     418     .06       0
#XS Ineff= 2 , 0
                          483.72         2040.33
Permanent Ineff=
       F       F
Bank Sta=403,418
XS Rating Curve= 0 ,0
Exp/Cntr=0.3,0.1

Type RM Length L Ch R = 1 ,25709.9 ,242,242.8,243.6
XS GIS Cut Line= 4
     1861491.746      147076.676     1861531.546      147344.565
     1861482.025      147560.609     1861464.192      147786.963
#Sta/Elev= 30
     5.1 2151.89    25.6 2146.12    35.8    2142      46 2136.81    56.3 2130.96
    66.5 2124.32    97.2 2101.66   107.4 2094.78   127.8 2083.58   158.5  2068.7
   219.9 2043.61   250.6 2030.04   260.4  2026.8   291.8 2018.35   306.3 2012.86
   312.5 2010.94   317.1 2010.18   324.6 2009.18   332.1  2009.2   364.4 2010.85
   502.3 2014.39   557.9 2016.65   570.2 2018.21   580.3 2022.28   631.1  2049.1
   641.2  2053.5   651.4 2055.58   661.3 2056.23   671.7 2059.11   719.5  2081.1
#Mann= 3 , 0 , 0
       0     .06       0   317.1    .045       0   332.1     .06       0
Bank Sta=317.1,332.1
XS Rating Curve= 0 ,0
Exp/Cntr=0.3,0.1

Type RM Length L Ch R = 1 ,25467.1 ,352.7,357,361.2
XS GIS Cut Line= 4
     1861366.565      146986.205     1861314.893      147264.386
     1861251.008        147502.5     1861207.648      147803.748
#Sta/Elev= 30
     2.8 2110.53    25.2 2106.91    86.9 2093.47   148.6    2078   179.5 2068.89
   230.9 2051.83   241.2 2047.71   261.8 2038.14   303.3 2016.85   313.8 2011.97
   324.2 2008.65   334.7 2007.52     411 2003.86   418.5 2003.62     426 2003.81
   491.8 2008.88   528.3 2012.43   537.1 2013.88   543.8 2015.97     554 2020.27
     581 2033.86   625.6 2057.47   635.4 2062.05   644.3 2064.32   656.2 2065.44
   666.5 2070.01   717.6 2105.62   758.4 2135.33   799.3 2164.22   833.8 2189.17
#Mann= 3 , 0 , 0
       0     .06       0     411    .045       0     426     .06       0
Bank Sta=411,426
XS Rating Curve= 0 ,0
Exp/Cntr=0.3,0.1

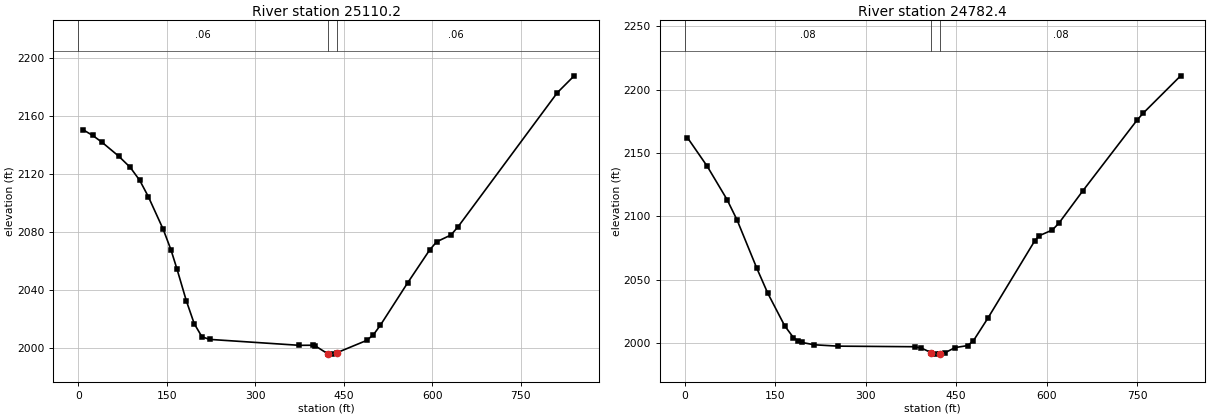
Type RM Length L Ch R = 1 ,25110.2 ,329.7,327.7,325.7
XS GIS Cut Line= 4
     1861211.612      146940.436     1860995.332      147201.614
     1860911.577      147362.934     1860738.386      147631.626
#Sta/Elev= 30
     8.9 2150.58    24.7 2146.78    40.6 2142.01    68.5 2132.53    88.2 2124.74
   104.3 2115.74   118.8 2104.53   144.1 2081.88   157.2 2067.73   167.5 2054.33
   183.3 2032.43   196.6 2016.72   209.7 2007.61   222.9 2005.84     375 2001.74
   397.8 2001.81   401.6 2001.38   423.3 1995.81   430.8 1995.66   438.3 1996.62
     489 2005.16   500.4 2009.11   511.8 2015.47   558.2 2044.86   595.5 2067.59
   607.5 2073.33   631.6 2077.98   643.6 2083.61   812.1 2176.43   840.5 2188.02
#Mann= 3 , 0 , 0
       0     .06       0   423.3    .045       0   438.3     .06       0
Bank Sta=423.3,438.3
XS Rating Curve= 0 ,0
Exp/Cntr=0.3,0.1

Type RM Length L Ch R = 1 ,24782.4 ,24775.4,24782.4,24789.3
XS GIS Cut Line= 4
     1860874.838      146801.134     1860731.911      146984.599
      1860626.85       147238.94     1860519.795      147534.458
#Sta/Elev= 30
     4.4 2162.18    37.3 2139.56    70.2 2113.29    86.7 2097.32   119.6  2059.1
   137.7 2039.48   165.8 2013.74   180.2  2004.5   187.4 2002.03   194.7  2000.6
   214.7  1998.8   253.8 1997.73   381.5 1997.26   392.4 1996.18   408.9 1992.58
   416.4 1991.43   423.9 1991.55   431.9 1992.59   448.1 1996.59     469 1998.14
   478.4 2001.83   502.4 2019.62   580.5  2080.9     588 2084.83   609.5 2089.29
   620.3 2094.65   659.5 2119.84   749.4  2175.6   760.1 2181.41   822.1 2210.81
#Mann= 3 , 0 , 0
       0     .08       0   408.9    .045       0   423.9     .08       0
Bank Sta=408.9,423.9
XS Rating Curve= 0 ,0
Exp/Cntr=0.3,0.1

Chan Stop Cuts=-1
Use User Specified Reach Order=0